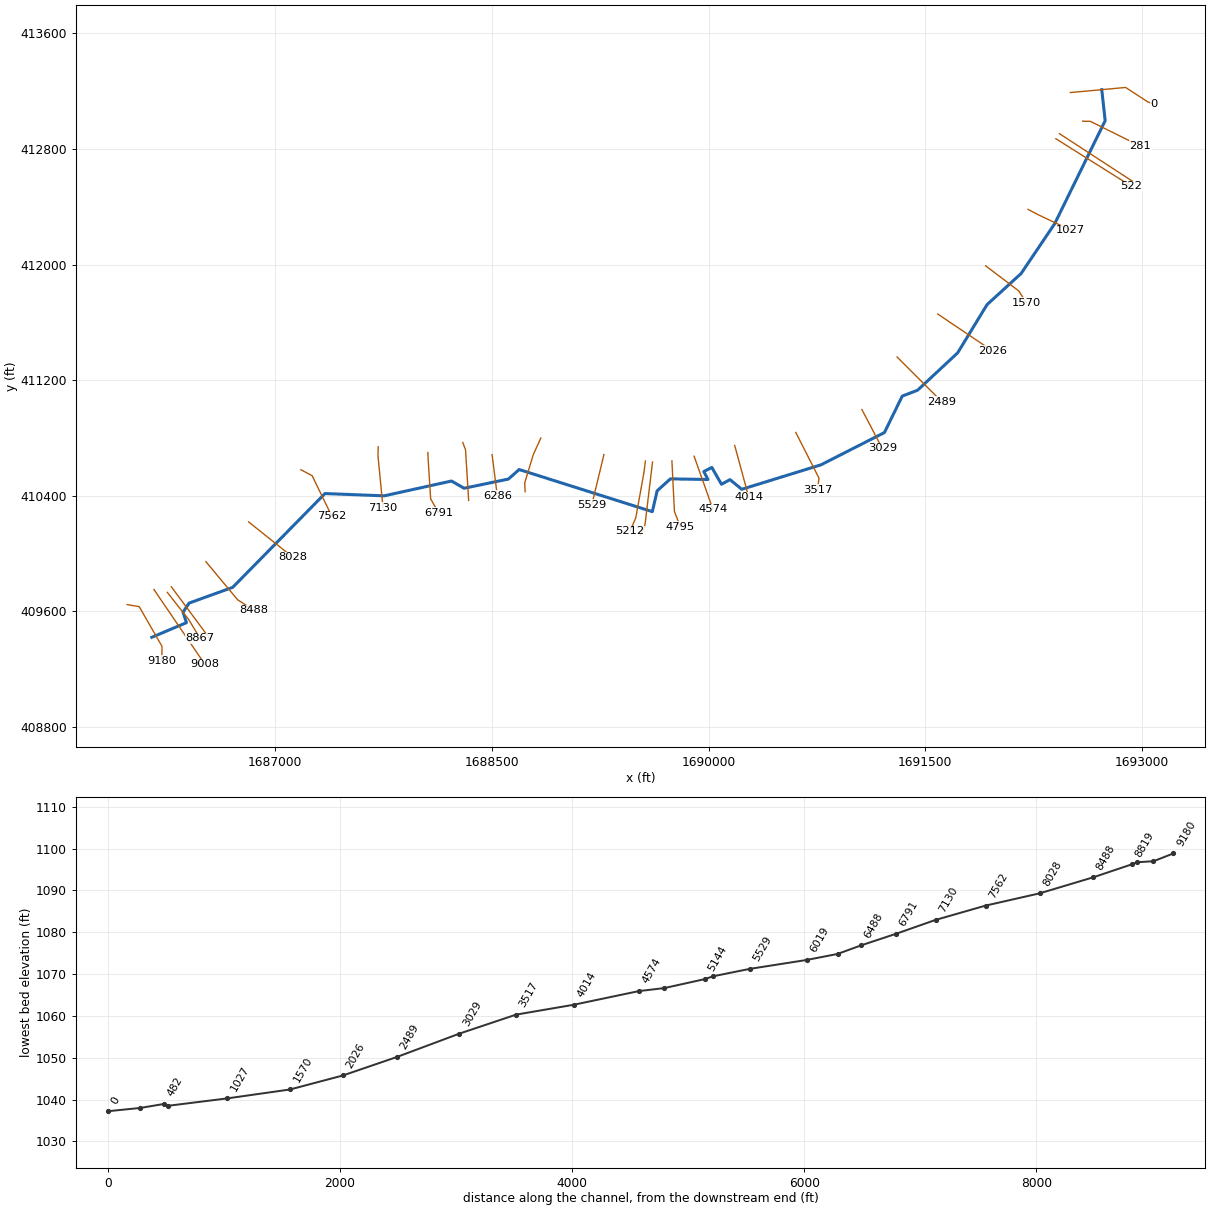
--- TEAGRDNFK.prj (project) ---

Proj Title=TEAGRDNFK
Current Plan=p01
Default Exp/Contr=0,0
English Units
Geom File=g01
Flow File=f01
Plan File=p01
BEGIN DESCRIPTION:
---------- MODELED AS PART OF WVEMD CTP PROGRAM, 2023----------
Stream Name: Tea Garden Fork
Flood Zone:  AFH
Wetzel County, WV
HEC-RAS Version: RAS 6.3
Vertical Datum: NAVD88
Projection: NAD 1983 StatePlane West Virginia S FIPS 4702 (US Feet)
Terrain: 1-meter West Virginia FEMA R3 South Central (collected 2018-2020)
Land Use: 2019 NLCD
Hydrologic Method:
WV SIR2010-5033 regression equations
Additional Model Notes:
Coincident Peak with LNGDRN. Normal Depth tie-in used.
END DESCRIPTION:
DSS Export Rating Curves= 0
DSS Export Rating Curve Sorted= 0
DSS Export Volume Flow Curves= 0
DXF OffsetX= 0
DXF OffsetY= 0
DXF ScaleX= 0
DXF ScaleY= 0

--- TEAGRDNFK.p01 (plan) ---

Plan Title=Floodplain
Program Version=6.30
Short Identifier=Floodplain
Geom File=g01
Flow File=f01
Subcritical Flow
K Sum by GR= 0
Std Step Tol= 0.01
Critical Tol= 0.01
Num of Std Step Trials= 20
Max Error Tol= 0.3
Flow Tol Ratio= 0.001
Split Flow NTrial= 30
Split Flow Tol= 0.02
Split Flow Ratio= 0.02
Log Output Level= 0
Friction Slope Method= 1
Unsteady Friction Slope Method= 2
Unsteady Bridges Friction Slope Method= 1
Parabolic Critical Depth
Global Vel Dist= 0 , 0 , 0
Global Log Level= 0
CheckData=False
Encroach Param=-1 ,0,0, 0
Mapping Interval=1HOUR
Computation Time Step Use Courant=        0
Computation Time Step Use Time Series=    0
Computation Time Step Count To Double=0
Computation Time Step Max Doubling=0
Computation Time Step Max Halving=0
Computation Time Step Residence Courant=0
Run HTab= 0
Run UNet= 0
Run Sediment= 0
Run PostProcess= 0
Run WQNet= 0
Run RASMapper=-1
UNET Theta= 0
UNET Theta Warmup= 0
UNET ZTol= 0
UNET ZSATol= 0
UNET MxIter= 0
UNET Max Iter WO Improvement= 0
UNET MaxInSteps= 0
UNET DtIC= 0
UNET DtMin= 0
UNET MaxCRTS= 0
UNET WFStab= 0
UNET SFStab= 0
UNET WFX= 1
UNET SFX= 1
UNET Gravity=32.17405
UNET 1D Methodology=Finite Difference
UNET DSS MLevel= 1
UNET Pardiso=0
UNET DZMax Abort= 0
UNET Use Existing IB Tables= 0
UNET Froude Reduction=False
UNET Froude Limit= 0
UNET Froude Power= 0
UNET D1 Cores= 0
UNET WindReference=Eulerian
UNET WindDragFormulation=Hsu (1988)
UNET D2 Coriolis=0
UNET D2 Cores= 0
UNET D2 Theta= 1
UNET D2 Theta Warmup= 1
UNET D2 Z Tol= 0.01
UNET D2 Volume Tol= 0.01
UNET D2 Max Iterations= 20
UNET D2 Equation= 0
UNET D2 RampUpFraction=0.1
UNET D2 TimeSlices= 1
UNET D2 Turbulence Formulation=Non-Conservative (original)
UNET D2 Eddy Viscosity=0.3
UNET D2 Transverse Eddy Viscosity=0.1
UNET D2 Smagorinsky Mixing=0
UNET D2 BCVolumeCheck=0
UNET D2 Cores=0
UNET D2 SolverType=PARDISO (Direct)
UNET D2 Minimum Iterations= 3
UNET D2 Maximum Iterations= 30
UNET D2 Restart Number= 10
UNET D2 Relaxation Coeff=1.3
UNET D2 SOR Precondition Iterations= 10
UNET D2 ILUT Maximum Fill= 8
UNET D2 ILUT Tolerance=1E-08
UNET D2 Convergence Tolerance=0.00001
UNET D1D2 MaxIter= 0
UNET D1D2 ZTol=0.01
UNET D1D2 QTol=0.1
UNET D1D2 MinQTol=1
Write IC File= 0
Write IC File at Fixed DateTime=0
Write IC File at Sim End=0
Echo Input=False
Echo Parameters=False
Echo Output=False
Write Detailed= 0
HDF Write Warmup=0
HDF Write Time Slices=0
HDF Flush=0
HDF Compression= 1
HDF Chunk Size= 1
HDF Spatial Parts= 1
HDF Use Max Rows=0
HDF Fixed Rows= 1
Calibration Method= 0
Calibration Iterations= 20
Calibration Max Change=0.05
Calibration Tolerance=0.2
Calibration Maximum=1.5
Calibration Minimum=0.5
Calibration Optimization Method= 1
WQ AD Non Conservative
WQ ULTIMATE=-1
WQ Max Comp Step=1HOUR
WQ Output Interval=15MIN
WQ Output Selected Increments= 0
WQ Output face flow=0
WQ Output face velocity=0
WQ Output face area=0
WQ Output face dispersion=0
WQ Output cell volume=0
WQ Output cell surface area=0
WQ Output cell continuity=0
WQ Output cumulative cell continuity=0
WQ Output face conc=0
WQ Output face dconc_dx=0
WQ Output face courant=0
WQ Output face peclet=0
WQ Output face adv mass=0
WQ Output face disp mass=0
WQ Output cell mass=0
WQ Output cell source sink temp=0
WQ Output nsm pathways=0
WQ Output nsm derived pathways=0
WQ Create Restart=0
WQ Fixed Restart=0
WQ System Summary=0
WQ Write To DSS=0
Sorting and Armoring Iterations= 10
XS Update Threshold= 0.02
Bed Roughness Predictor= 0
Hydraulics Update Threshold= 0.02
Energy Slope Method= 1
Volume Change Method= 1
Sediment Retention Method= 0
Sediment TS Multiplier= 1
Warm Up Method= 0
XS Weighting Method= 0
Number of US Weighted Cross Sections= 1
Number of DS Weighted Cross Sections= 1
Upstream XS Weight=0
Main XS Weight=1
Downstream XS Weight=0
Number of DS XS's Weighted with US Boundary= 1
Upstream Boundary Weight= 1
Weight of XSs Associated with US Boundary= 0
Number of US XS's Weighted with DS Boundary= 1
Downstream Boundary Weight= 0.5
Weight of XSs Associated with DS Boundary= 0.5
Percentile Method= 0
Sediment Output Level= 3
Mass or Volume Output= 0
Output Increment Type= 1
Profile and TS Output Increment= 1
Transport Output Increment 1
XS Output Flag= 0
XS Output Increment= 10
Read HDF5 Sediment Hotstart= 0
Sediment Hotstart Type= 0
Write Gradation File= 0
Read Gradation Hotstart= 0
Write HDF5 File= 1
Write Binary Output= 1
Write DSS Sediment File= 0
DSS Sediment Output Type= 1
SV Curve= 0
Specific Gage Flag= 0
Subcell Erosion Methods= 0
Subcell Deposition Methods= 0
Advection Scheme= 1
Matrix Solver= 0
Implicit Weighting Factor= 1
Maximum Outer Loop Convergence Iterations= 5
Convergence Maximum Absolute= 0.001
Convergence RMSE= 0.0001
Grain Fractions Max Abs Error= 0.001
Max Subgrid Regions= 1
Max Subgrid Length Scale= 3.402823E+38
Initial Layer Thickness= 3.402823E+38
Min Layer Thickness= 3.402823E+38
Max Layer Thickness= 3.402823E+38
Number of Layers= 5

--- TEAGRDNFK.f01 (steady flow) ---

Flow Title=Flow
Program Version=6.30
Number of Profiles= 1
Profile Names=F01pct
River Rch & RM=TEAGRDNFK,Main,9180
     953
River Rch & RM=TEAGRDNFK,Main,8028
    1060
River Rch & RM=TEAGRDNFK,Main,5529
    1280
Boundary for River Rch & Prof#=TEAGRDNFK,Main            , 1
Up Type= 0
Dn Type= 3
Dn Slope=0.0028
DSS Import GetInterval= 0
DSS Import GetPeak= 0
DSS Import FillOption= 0

--- TEAGRDNFK.g01 (geometry) ---

Geom Title=Geometry
Program Version=6.31

River Reach=TEAGRDNFK       ,Main
Reach XY= 30
 1686146.4857624409420.231984421     1686386.009      409521.583
     1686362.086       409593.66     1686404.028      409656.729
     1686706.321      409766.089     1687344.771      410415.101
     1687754.559      410399.257     1688220.581      410501.782
     1688307.882      410451.762     1688614.835      410515.452
     1688689.088      410581.316     1689610.994      410289.873
     1689644.221      410433.668     1689736.169      410516.736
     1689995.973       410512.44     1689967.329      410567.437
     1690022.899      410595.795     1690089.926      410479.212
     1690148.647      410511.581     1690229.997      410444.553
     1690778.249       410613.84     1691217.653      410837.266
      1691341.11      411089.622     1691447.094      411130.297
     1691724.657      411388.955     1691928.031      411722.661
      1692164.06      411938.353     1692396.366      412282.944
     1692745.826      412996.1871692722.31696848413210.716884516

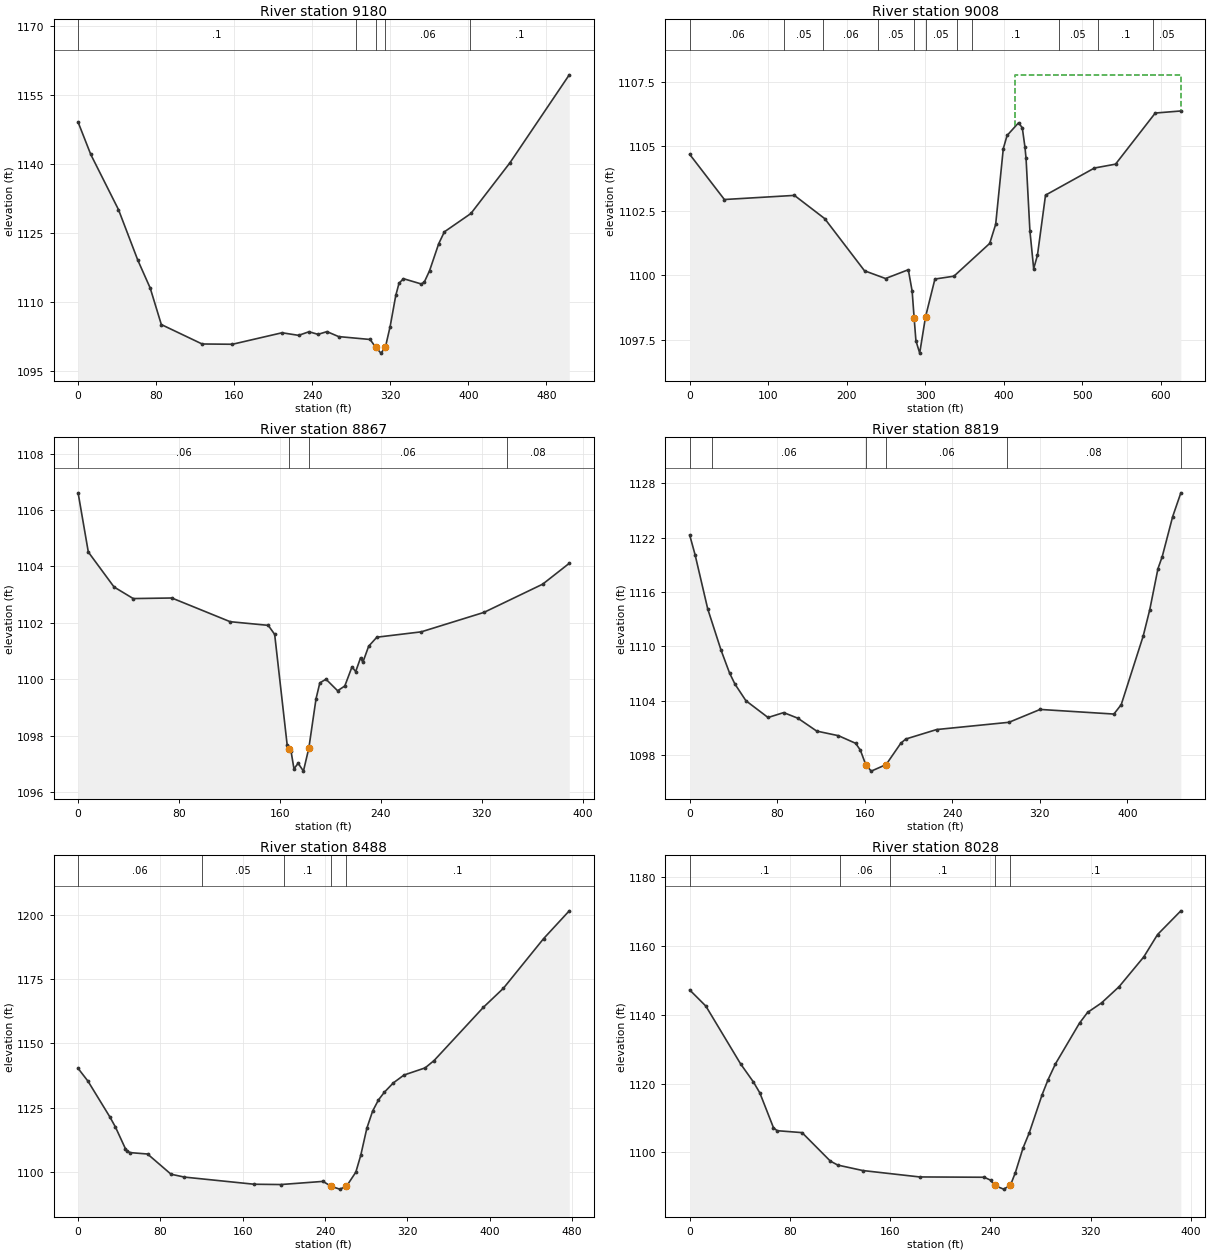
Type RM Length L Ch R = 1 ,9180    ,170.8,171.9,172.6
XS GIS Cut Line= 4
1685975.35656641409646.6485176561686059.25216368 409631.89764341
1686216.90213218409357.162610587 1686215.0582729409255.750350149
#Sta/Elev= 30
       0 1149.12      13 1142.08    41.4 1130.08    61.2 1119.08    73.9 1113.01
    85.3 1105.07   127.1 1100.84   158.2 1100.78     209 1103.28     226 1102.72
   236.6  1103.5   245.9 1102.94   255.1 1103.53     267 1102.45   299.3 1101.82
   305.1 1100.09   310.4 1098.85   314.91100.104   319.8 1104.63   325.6 1111.41
   328.9 1114.06   333.5 1115.05   351.9 1113.89   354.9 1114.35   360.2 1116.78
   369.6 1122.67   375.4 1125.25   402.6 1129.24   442.6 1140.28   503.4 1159.42
#Mann= 5 ,-1,0
       0      .1       0  285.18     .06       0   305.1    .045       0
   314.9     .06       0  401.94      .1       0
Bank Sta=305.1,314.9
XS Rating Curve= 0 ,0
Exp/Cntr(USF)=0,0
Exp/Cntr=0.3,0.1

Type RM Length L Ch R = 1 ,9008    ,138.5,141.2,139.3
XS GIS Cut Line= 2
  1686160.971734409750.7468940831686513.14885661409233.544365849
#Sta/Elev= 30
       0 1104.68    44.2 1102.93   133.4 1103.09     172 1102.19   222.7 1100.17
   249.5 1099.87   278.5 1100.21   283.4 1099.38   285.91098.351   288.2 1097.46
     293 1096.98   300.4 1098.38   312.4 1099.85   336.6 1099.96   382.2 1101.23
   389.8 1101.97   399.5  1104.9   404.3 1105.41   418.9  1105.9   423.7 1105.71
   427.1 1104.96   428.5 1104.52   433.4 1101.72   438.2 1100.25     443 1100.77
   453.3  1103.1   515.6 1104.15   542.5  1104.3   593.1 1106.28   625.7 1106.36
#Mann= 11 ,-1,0
       0     .06       0     120     .05       0     170     .06       0
     240     .05       0   285.9    .045       0   300.4     .05       0
     340     .06       0     360      .1       0     470     .05       0
     520      .1       0     590     .05       0
#XS Ineff= 2 , 0
                          414.81         1107.76
Permanent Ineff=
       F       F
Bank Sta=285.9,300.4
XS Rating Curve= 0 ,0
Exp/Cntr(USF)=0,0
Exp/Cntr=0.3,0.1

Type RM Length L Ch R = 1 ,8867    ,45.9,47.4,44.1
XS GIS Cut Line= 3
 1686253.5504162409730.8868349991686402.08352492409542.403441862
1686478.91099495 409414.35765848
#Sta/Elev= 30
       0 1106.61     8.1 1104.51    28.5 1103.27    43.7 1102.86    74.3 1102.88
   120.5 1102.04   150.7 1101.91   155.8 1101.59   165.7 1097.67   166.9 1097.54
   168.7 1097.47   171.1 1096.82   174.4 1097.02   178.6 1096.74   182.9 1097.56
   188.6 1099.31   191.6 1099.87   196.5    1100   205.7 1099.59   211.4 1099.76
   217.1 1100.44     220 1100.27   223.9 1100.76   225.7  1100.6   230.3 1101.17
   236.8 1101.49     272 1101.68   321.7 1102.37   368.2 1103.37   389.3 1104.11
#Mann= 4 ,-1,0
       0     .06       0   166.9    .045       0   182.9     .06       0
  339.98     .08       0
Bank Sta=166.9,182.9
XS Rating Curve= 0 ,0
Exp/Cntr(USF)=0,0
Exp/Cntr=0.3,0.1

Type RM Length L Ch R = 1 ,8819    ,330.6,331.2,329.7
XS GIS Cut Line= 2
1686281.20830541409769.8127531471686548.56790111409409.235827145
#Sta/Elev= 30
       0 1122.28     4.9 1120.12    16.5 1114.12    28.7 1109.56    36.4 1107.06
    41.4 1105.82    51.4 1103.99    71.6 1102.14    85.9 1102.68    98.9 1102.06
   116.1 1100.64     136 1100.13   151.7 1099.29     156 1098.53   160.9 1096.94
   165.9 1096.22   179.5 1096.94   192.9 1099.29   197.4 1099.76   225.7 1100.81
   291.8 1101.61   320.3 1103.03   387.7 1102.52   394.4 1103.56   414.5 1111.14
   420.5 1114.05     428 1118.58   431.9 1119.91   441.4 1124.31   448.9 1126.94
#Mann= 6 ,-1,0
       0      .1       0      20     .06       0   160.9    .045       0
   179.5     .06       0     290     .08       0  448.88      .1       0
Bank Sta=160.9,179.5
XS Rating Curve= 0 ,0
Exp/Cntr(USF)=0,0
Exp/Cntr=0.3,0.1

Type RM Length L Ch R = 1 ,8488    ,458.8,460.3,461.2
XS GIS Cut Line= 3
1686520.35735997409943.9082265061686739.57174112409680.646095874
 1686852.2520305409606.891724647
#Sta/Elev= 30
       0 1140.27     9.6 1135.28    30.9  1121.3    36.3 1117.36      46  1108.9
    47.7 1108.03    50.5 1107.39    67.5 1106.84    90.3 1098.95   103.3 1097.83
     171 1095.04     197 1094.92     238 1096.15   245.9 1094.21   254.2 1093.13
   260.7 1094.17   269.9 1099.77   274.7 1106.38   280.6 1116.91   286.2 1123.59
   291.9 1127.97   297.6 1130.96   306.3  1134.6   316.7 1137.68   337.2 1140.46
   345.9 1143.32   393.9 1164.14   413.3 1171.55   452.3 1190.91   477.3 1201.79
#Mann= 5 ,-1,0
       0     .06       0     120     .05       0     200      .1       0
   245.9    .045       0   260.7      .1       0
Bank Sta=245.9,260.7
XS Rating Curve= 0 ,0
Exp/Cntr(USF)=0,0
Exp/Cntr=0.3,0.1

Type RM Length L Ch R = 1 ,8028    ,469.5,465.5,462.8
XS GIS Cut Line= 2
1686816.36406464410218.8486079111687122.64957849409974.025070085
#Sta/Elev= 30
       0 1147.19    12.9  1142.5    40.6 1125.73    50.9 1120.43      56 1117.27
    66.9 1107.14    69.8 1106.29    89.7 1105.73   112.3 1097.45   118.2  1096.3
   138.2 1094.71   183.6 1092.85   235.2 1092.76   240.4 1091.87   243.4 1090.37
   250.6 1089.31     2561090.399     260 1094.12   266.1 1101.25   271.1 1105.69
   281.3 1116.71   286.1 1121.12     292 1125.72   311.2 1137.56   317.6 1140.65
   328.8 1143.43   342.8 1148.14   362.5 1156.79   373.5 1163.29   392.1 1170.18
#Mann= 5 ,-1,0
       0      .1       0     120     .06       0     160      .1       0
   243.4    .045       0     256      .1       0
Bank Sta=243.4,256
XS Rating Curve= 0 ,0
Exp/Cntr(USF)=0,0
Exp/Cntr=0.3,0.1

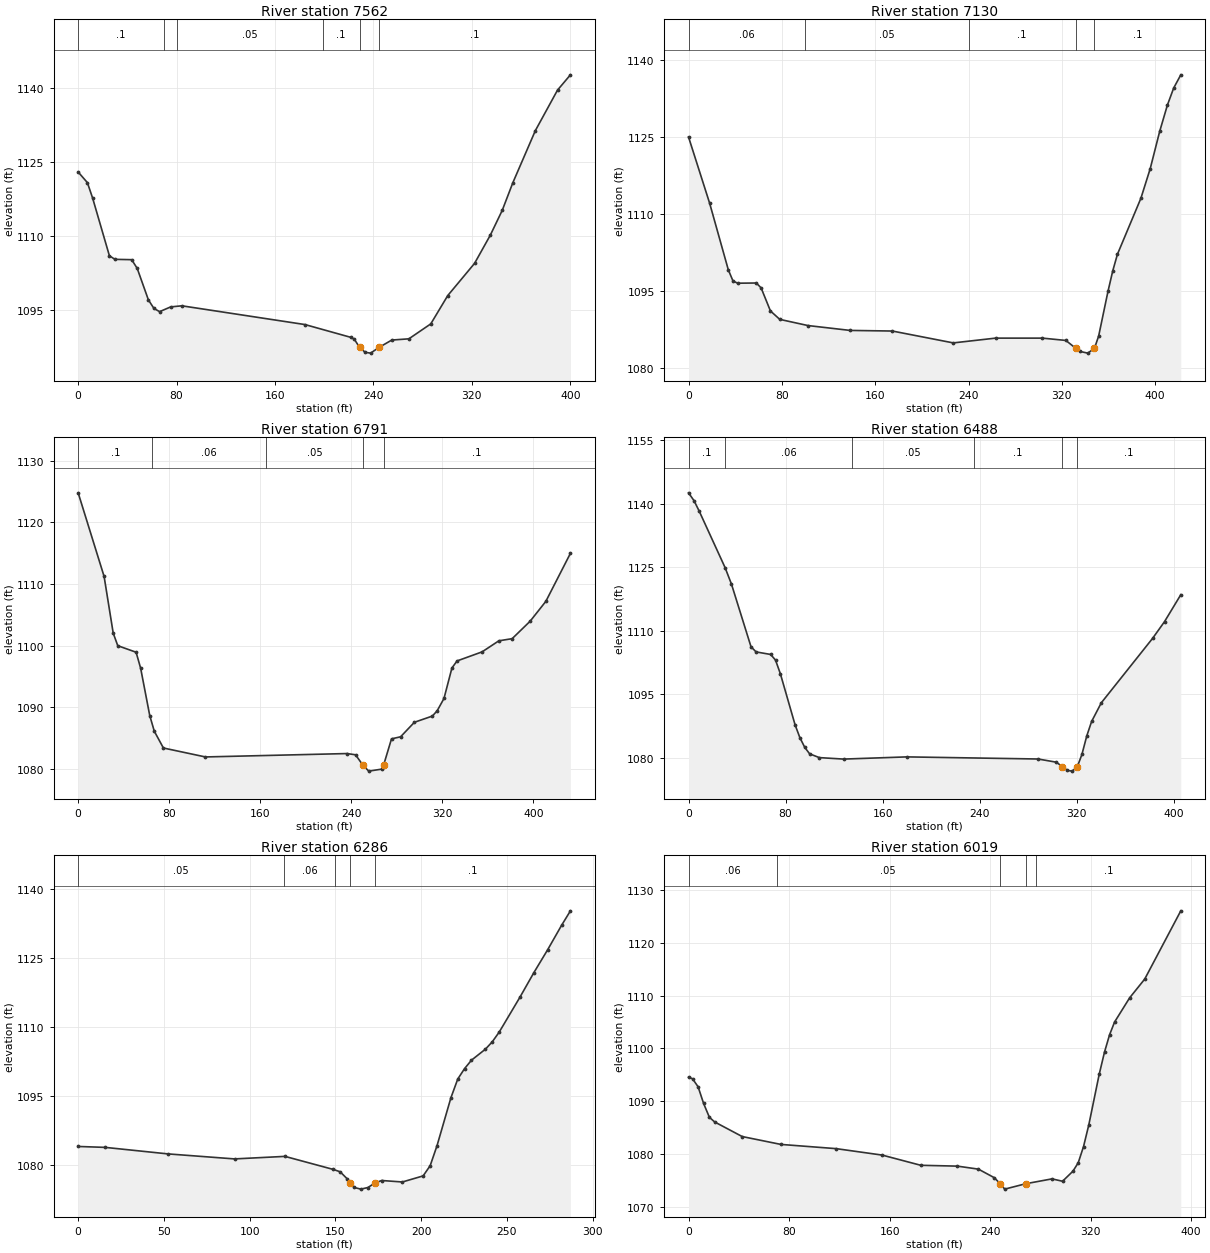
Type RM Length L Ch R = 1 ,7562    ,434,432,429.1
XS GIS Cut Line= 3
1687177.73743215410580.2651406331687256.14754806410538.446412147
1687392.05841564410258.410283892
#Sta/Elev= 30
       0 1122.98     7.5 1120.83    11.8 1117.67    25.4 1106.05    29.9 1105.33
    43.5 1105.26      48  1103.5    57.1 1097.13    61.6 1095.41    66.2 1094.76
    75.2 1095.72    84.3 1095.94   184.4 1092.15     222 1089.54   224.4  1089.2
   228.8 1087.53   233.3 1086.54   237.7 1086.38   244.5 1087.53   254.9 1089.02
   268.8 1089.27   286.6 1092.29   300.4 1098.01   322.2 1104.52     335 1110.22
   344.7 1115.24   353.3 1120.81   371.6 1131.34   389.6 1139.52   400.1 1142.61
#Mann= 6 ,-1,0
       0      .1       0      70     .06       0      80     .05       0
  198.86      .1       0   228.8    .045       0   244.5      .1       0
Bank Sta=228.8,244.5
XS Rating Curve= 0 ,0
Exp/Cntr(USF)=0,0
Exp/Cntr=0.3,0.1

Type RM Length L Ch R = 1 ,7130    ,339.1,339.1,338.4
XS GIS Cut Line= 3
1687713.45971373410738.6553161971687711.61585445410678.729889574
1687746.59073044410318.490953222
#Sta/Elev= 30
       0 1125.02    18.1 1112.12    34.1 1099.16    38.1    1097    42.1 1096.56
    58.1  1096.6    62.2 1095.65    70.2 1091.16    78.2 1089.52   102.3 1088.32
   138.5 1087.37   174.7 1087.25   226.9 1084.94   263.1 1085.87   303.3 1085.87
   323.4 1085.42     3321083.866   335.4 1083.28   342.2 1082.95   347.91083.883
   351.5 1086.28   359.5 1094.98   363.6 1098.98   367.6  1102.2   387.7 1113.09
   395.7 1118.87   403.8 1126.11   410.4 1131.22   415.8 1134.55   421.9 1137.12
#Mann= 5 ,-1,0
       0     .06       0   99.95     .05       0  239.95      .1       0
     332    .045       0   347.9      .1       0
Bank Sta=332,347.9
XS Rating Curve= 0 ,0
Exp/Cntr(USF)=0,0
Exp/Cntr=0.3,0.1

Type RM Length L Ch R = 1 ,6791    ,300.6,303,301.3
XS GIS Cut Line= 4
1688057.17885906410699.3474738361688059.02271834410654.172921459
1688076.53938151410378.5159589961688130.93323029410281.713346759
#Sta/Elev= 30
       0 1124.78    22.8 1111.22    30.8 1102.03    34.8 1099.99    50.9 1098.93
    54.9 1096.34    62.9 1088.66    66.9 1086.12    74.9  1083.4   111.8 1081.95
   236.2  1082.5   243.7  1082.3   250.1 1080.64   255.3 1079.65   267.3 1079.99
   268.4 1080.65   275.3 1084.88   283.3 1085.22   295.4 1087.57   311.2 1088.58
   315.4 1089.43   321.4 1091.43   328.4 1096.38   332.9 1097.52   354.9 1098.99
   369.6 1100.78   381.3 1101.13   397.1 1103.96   410.9 1107.18   432.5 1114.97
#Mann= 5 ,-1,0
       0      .1       0   65.21     .06       0  165.21     .05       0
   250.1    .045       0   268.4      .1       0
Bank Sta=250.1,268.4
XS Rating Curve= 0 ,0
Exp/Cntr(USF)=0,0
Exp/Cntr=0.3,0.1

Type RM Length L Ch R = 1 ,6488    ,200.8,201.8,201.5
XS GIS Cut Line= 3
1688298.84734879410768.8017831111688317.93129234 410717.35810918
1688339.50444593410367.209231777
#Sta/Elev= 30
       0 1142.53     4.5 1140.69     8.8 1138.21    30.1  1124.9    35.4 1120.98
    51.5  1106.2    55.7 1104.99    67.7 1104.39    71.7 1103.05    75.7 1099.83
    87.8  1087.8    91.8 1084.73    95.8 1082.46    99.8 1080.94   107.8 1080.05
   127.8  1079.7   179.9 1080.22   288.1 1079.72   303.1 1078.97  308.05 1077.92
   312.2 1077.03   316.2 1076.86  320.45 1077.92   324.2 1080.79   328.2 1085.16
   332.2 1088.58   340.2 1092.99   382.4 1108.17   392.3 1112.14   405.7 1118.49
#Mann= 6 ,-1,0
       0      .1       0      30     .06       0  134.87     .05       0
  234.87      .1       0  308.05    .045       0  320.45      .1       0
Bank Sta=308.05,320.45
XS Rating Curve= 0 ,0
Exp/Cntr(USF)=0,0
Exp/Cntr=0.3,0.1

Type RM Length L Ch R = 1 ,6286    ,268.9,266.9,259.5
XS GIS Cut Line= 2
1688501.81869549410684.1777476061688537.77395147410399.301488739
#Sta/Elev= 30
       0 1084.07    15.8 1083.87    52.3 1082.46    91.2 1081.37   120.6 1081.92
   148.8 1079.09   152.8 1078.58   156.9 1077.06   158.8 1076.14   160.9 1075.18
   164.9 1074.82     169 1075.17     173 1076.13     177 1076.69   189.1 1076.37
   201.2 1077.69   205.3  1079.9   209.3 1084.24   217.4 1094.63   221.4  1098.7
   225.4 1100.97   229.4 1102.78   237.5 1105.16   241.5 1106.75   245.6 1108.89
   257.7 1116.46   265.7 1121.71   273.8 1126.71   281.9 1131.99   287.1 1135.16
#Mann= 5 ,-1,0
       0     .05       0     120     .06       0     150      .1       0
   158.8    .045       0     173      .1       0
Bank Sta=158.8,173
XS Rating Curve= 0 ,0
Exp/Cntr(USF)=0,0
Exp/Cntr=0.3,0.1

Type RM Length L Ch R = 1 ,6019    ,488.3,490,489.6
XS GIS Cut Line= 4
1688839.24494386410799.4189526491688786.69495436410684.177747606
1688727.69145738410488.728663852 1688730.4572463410427.881307589
#Sta/Elev= 30
       0 1094.57     3.2 1094.26     7.6 1092.75      12 1089.59    16.6 1086.97
    20.8 1086.09    42.7 1083.33    73.5 1081.84   117.5 1081.04   154.1 1079.82
   184.8 1077.89     214 1077.73   230.7 1077.16   243.3 1075.54   247.9 1074.43
   251.6 1073.38   268.3  1074.4   289.2 1075.32   297.6 1074.87   305.9 1076.78
   310.1 1078.38   314.3 1081.43   318.5 1085.54   326.8 1095.14     331 1099.32
     335 1102.57     339    1105     351 1109.58     363 1113.13   391.7 1126.04
#Mann= 5 ,-1,0
       0     .06       0      70     .05       0   247.9    .045       0
   268.3     .05       0  276.66      .1       0
Bank Sta=247.9,268.3
XS Rating Curve= 0 ,0
Exp/Cntr(USF)=0,0
Exp/Cntr=0.3,0.1

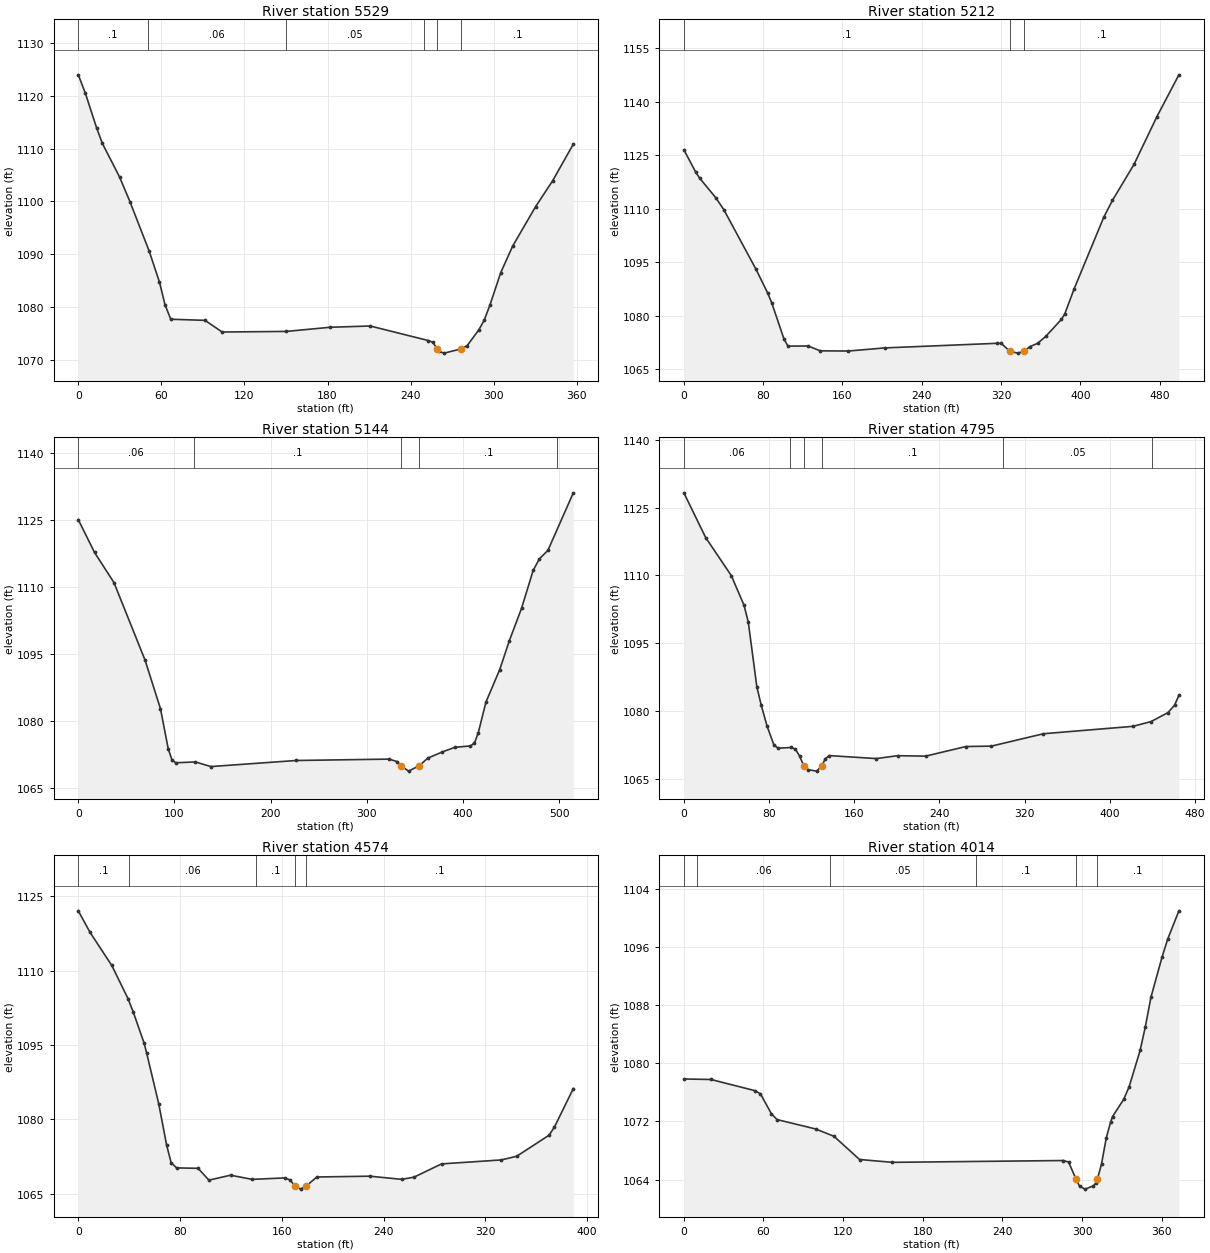
Type RM Length L Ch R = 1 ,5529    ,317.1,317.4,317.7
XS GIS Cut Line= 2
1689276.12296631410685.4946868541689192.22736904410337.927212443
#Sta/Elev= 30
       0 1123.97     5.1 1120.49    13.3 1113.87    17.4 1110.97    29.8 1104.62
    37.3 1099.95    51.2 1090.57    58.6 1084.73    62.7 1080.36    66.8 1077.67
    91.5 1077.46   103.9 1075.25     150 1075.36     182 1076.15   210.8 1076.39
   252.7 1073.64   256.1 1073.31   259.11072.064   260.2 1071.56   264.3 1071.25
   276.7 1072.07   280.8 1072.66   289.2 1075.63   293.1 1077.46   297.3 1080.36
     305 1086.44   313.7 1091.53   330.2 1098.97   342.5 1103.87   357.5 1110.84
#Mann= 6 ,-1,0
       0      .1       0      50     .06       0     150     .05       0
     250      .1       0   259.1    .045       0   276.7      .1       0
Bank Sta=259.1,276.7
XS Rating Curve= 0 ,0
Exp/Cntr(USF)=0,0
Exp/Cntr=0.3,0.1

Type RM Length L Ch R = 1 ,5212    ,66.4,67.5,67.9
XS GIS Cut Line= 4
1689563.27782504 410640.524080141689552.98149866 410561.10049885
1689496.64135398410247.6444211321689456.74373326410154.974469558
#Sta/Elev= 30
       0 1126.52    12.1 1120.17    16.1  1118.5    32.3 1113.02    40.3 1109.72
    72.6 1093.09    84.7 1086.25    88.8 1083.47     101 1073.44     105 1071.44
   125.4 1071.47   137.6 1070.11     166 1070.06   202.6 1070.93   316.4 1072.23
   320.4 1072.18  328.78 1070.02   336.7 1069.47   343.71070.026   348.9 1071.26
     357 1072.22   365.1 1074.15     381 1078.95   384.5 1080.56   393.6 1087.36
   423.7 1107.59   432.4 1112.29   454.2  1122.4   477.4 1135.84   499.5 1147.53
#Mann= 3 ,-1,0
       0      .1       0  328.78    .045       0   343.7      .1       0
Bank Sta=328.78,343.7
XS Rating Curve= 0 ,0
Exp/Cntr(USF)=0,0
Exp/Cntr=0.3,0.1

Type RM Length L Ch R = 1 ,5144    ,341.4,349,347.9
XS GIS Cut Line= 3
1689612.44740586410633.3535162711689560.15206253410198.474840314
1689529.47373822410128.340946615
#Sta/Elev= 30
       0 1125.11    16.9 1117.77    37.1 1111.02    69.3 1093.73    85.4 1082.82
    93.5 1073.81    97.5 1071.26   101.5 1070.69   121.7 1070.88   137.8 1069.84
   226.4  1071.2   323.1 1071.51   331.2 1070.97   335.5 1070.04   343.3 1068.82
   354.4 1070.03   363.4 1071.74   378.6 1073.13   391.6 1074.16   407.7 1074.46
   411.8  1075.1   415.8  1077.4   423.8 1084.29   438.1 1091.55   448.1 1098.01
   460.8 1105.27   472.9 1113.77   479.4 1116.35   488.2 1118.24   514.6 1131.12
#Mann= 5 ,-1,0
       0     .06       0     120      .1       0   335.5    .045       0
   354.4      .1       0  498.01     .06       0
Bank Sta=335.5,354.4
XS Rating Curve= 0 ,0
Exp/Cntr(USF)=0,0
Exp/Cntr=0.3,0.1

Type RM Length L Ch R = 1 ,4795    ,219.2,221.2,221
XS GIS Cut Line= 3
1689746.58672314 410641.001067681689764.00094968410291.692170616
1689804.97560036410184.133712575
#Sta/Elev= 30
       0 1128.31    20.5 1118.39    44.5 1109.99    56.5 1103.41    60.5 1099.67
    68.5 1085.37    72.6  1081.3    78.2 1076.58    84.6 1072.44    88.6 1071.74
   100.6 1071.91   104.6 1071.55   108.6 1070.05   112.6 1067.84   116.6    1067
   124.6 1066.67   129.61067.853   132.6 1069.36   136.6 1070.11   180.7 1069.45
   200.7 1070.09     227 1069.99   264.8 1072.12   288.8 1072.21   337.6 1074.95
   421.6 1076.59   438.7 1077.65   454.6 1079.64   460.8  1081.3   464.8 1083.46
#Mann= 6 ,-1,0
       0     .06       0     100      .1       0   112.6    .045       0
   129.6      .1       0     300     .05       0  439.74      .1       0
Bank Sta=112.6,129.6
XS Rating Curve= 0 ,0
Exp/Cntr(USF)=0,0
Exp/Cntr=0.3,0.1

Type RM Length L Ch R = 1 ,4574    ,552.7,560.1,554.8
XS GIS Cut Line= 2
1689900.16059915410673.3429664951690030.42925733410306.599355565
#Sta/Elev= 30
       0 1122.08     9.3 1117.71    26.3 1111.07    39.1 1104.37    43.3 1101.59
    51.8 1095.36    53.8 1093.32    63.2 1083.21    69.5 1074.77      73 1071.27
    77.3 1070.22    94.2 1070.14   102.7 1067.75   119.7 1068.75   136.7 1067.91
   162.2  1068.2   166.4 1067.81   170.41066.581   174.9 1065.94   179.1 1066.56
   187.6 1068.39   229.2 1068.55   254.3 1067.91     264 1068.36   285.6 1071.03
   332.6 1071.83   344.7 1072.57   370.2 1076.83   374.4 1078.48   389.2 1086.23
#Mann= 5 ,-1,0
       0      .1       0      40     .06       0     140      .1       0
   170.4    .045       0   179.1      .1       0
Bank Sta=170.4,179.1
XS Rating Curve= 0 ,0
Exp/Cntr(USF)=0,0
Exp/Cntr=0.3,0.1

Type RM Length L Ch R = 1 ,4014    ,494.2,496.8,498.9
XS GIS Cut Line= 2
1690181.14324183410748.2630665351690278.96919597410388.323296351
#Sta/Elev= 30
       0 1077.85    20.4 1077.78    53.6 1076.24    57.7  1075.8      66 1073.05
    70.2 1072.26    99.2 1070.97     113 1069.97   132.4 1066.76   157.2 1066.37
   285.9 1066.62   289.9 1066.41   295.5 1064.05   298.2 1063.07   302.3 1062.68
   308.6 1063.13   310.6 1063.51  311.62 1064.07   314.7 1066.14   318.3 1069.76
   321.6 1071.93     323 1072.67   331.4 1075.04   335.5 1076.78   343.8 1081.79
   347.7 1085.03     352 1089.15   360.3 1094.63   364.5 1097.08     373 1101.01
#Mann= 6 ,-1,0
       0      .1       0      10     .06       0     110     .05       0
     220      .1       0   295.5    .045       0  311.62      .1       0
Bank Sta=295.5,311.62
XS Rating Curve= 0 ,0
Exp/Cntr(USF)=0,0
Exp/Cntr=0.3,0.1

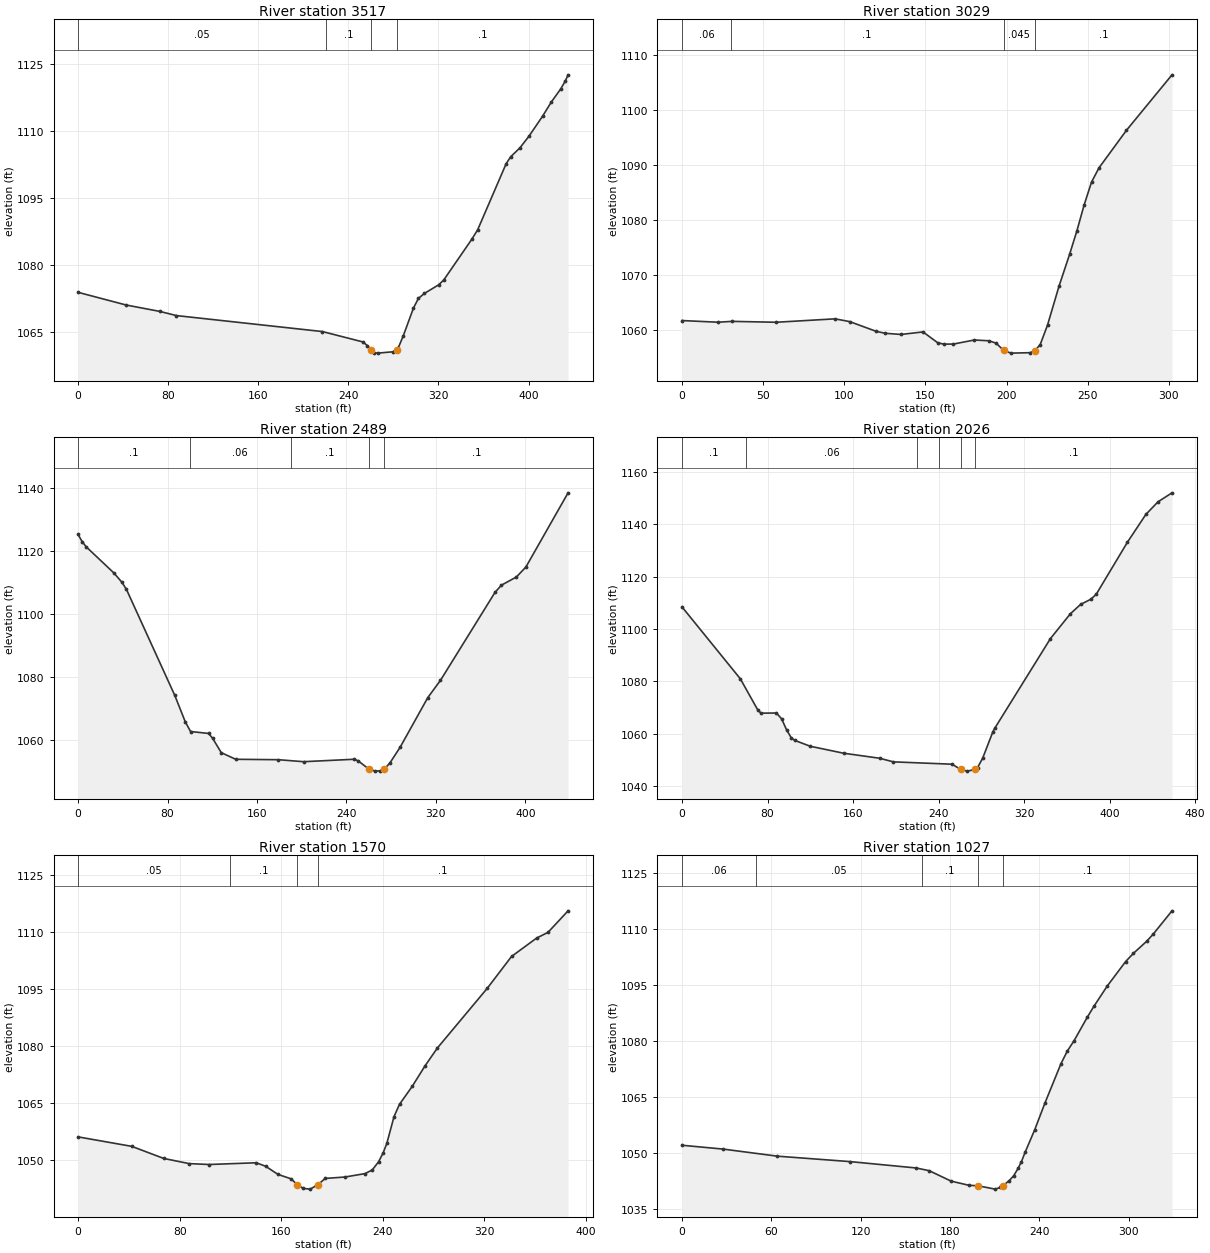
Type RM Length L Ch R = 1 ,3517    ,487.6,488.5,487.8
XS GIS Cut Line= 3
1690604.21880252410838.0845088431690764.70285103410521.669150798
1690754.45918835410441.996218916
#Sta/Elev= 30
       0 1073.94    42.7  1071.1    72.5 1069.67    87.4 1068.73     217 1065.15
   252.9 1062.83     257 1061.99     260 1061.08   262.9 1060.43   265.9 1060.32
   279.8 1060.62   282.91061.045   284.3 1061.48   288.8 1064.21   297.8  1070.4
   302.2 1072.57   307.6 1073.71   320.2 1075.62   324.7  1076.7   349.6 1085.82
   354.8 1087.93   380.1 1102.74   384.2 1104.32   392.2 1106.26   400.3 1108.88
   412.4 1113.37   420.2 1116.56   428.5 1119.48   432.6 1121.25   435.1 1122.66
#Mann= 4 ,-1,0
       0     .05       0     220      .1       0     260    .045       0
   282.9      .1       0
Bank Sta=260,282.9
XS Rating Curve= 0 ,0
Exp/Cntr(USF)=0,0
Exp/Cntr=0.3,0.1

Type RM Length L Ch R = 1 ,3029    ,534.2,539.7,539.1
XS GIS Cut Line= 2
1691061.96156797 410996.03380341 1691202.0948733 410728.67420771
#Sta/Elev= 30
       0 1061.71      22 1061.41    30.9 1061.56    58.1  1061.4    94.3 1062.02
   103.3 1061.52   119.7 1059.74   125.3 1059.39   134.9 1059.18   148.5 1059.64
   157.5 1057.68   161.2 1057.42   167.2 1057.43   180.1 1058.17   189.1 1058.03
   193.6 1057.59   198.1 1056.28   202.7 1055.78   214.6 1055.86   217.5 1056.25
   220.7 1057.34   225.2 1060.88   232.3 1067.98   238.8 1073.76   243.3 1078.04
   247.8 1082.79   252.3  1086.9   256.9  1089.5   273.8 1096.33   301.9 1106.44
#Mann= 4 ,-1,0
       0     .06       0      30      .1       0   198.1    .045       0
   217.5      .1       0
Bank Sta=198.1,217.5
XS Rating Curve= 0 ,0
Exp/Cntr(USF)=0,0
Exp/Cntr=0.3,0.1

Type RM Length L Ch R = 1 ,2489    ,461.9,463.3,464.6
XS GIS Cut Line= 2
1691305.50095955411360.2521910161691615.34013909411050.413011475
#Sta/Elev= 30
       0 1125.17     3.7 1122.87     7.3 1121.24      32 1112.98    39.2 1110.03
    43.3 1107.74    86.5 1074.18    95.8 1065.88   100.6 1062.73   116.8 1062.12
   120.4 1060.55   128.1 1056.03     141 1053.93   179.1  1053.8   201.7 1053.17
   246.9 1053.94   250.5 1053.44   259.8  1050.9   265.5 1050.18   270.3 1050.29
     274 1050.87   278.8 1052.72   288.1 1057.79   312.8  1073.5   324.1 1078.94
   372.9 1106.83   378.6 1109.09     392 1111.69   400.5 1114.85   438.2 1138.35
#Mann= 5 ,-1,0
       0      .1       0     100     .06       0     190      .1       0
   259.8    .045       0     274      .1       0
Bank Sta=259.8,274
XS Rating Curve= 0 ,0
Exp/Cntr(USF)=0,0
Exp/Cntr=0.3,0.1

Type RM Length L Ch R = 1 ,2026    ,456.1,455.9,455.2
XS GIS Cut Line= 2
1691586.82096129411657.7186634871691966.97466484411401.627096725
#Sta/Elev= 30
       0 1108.45    54.6    1081    70.9 1069.12    73.9  1067.9    88.4 1067.96
    93.2 1065.73      98  1061.4   102.3 1058.46   105.5 1057.51   119.9 1055.28
   151.1 1052.62   184.8  1050.7   197.7 1049.32   252.7 1048.42   260.7 1046.42
   266.8 1045.78  274.47 1046.42   276.5 1047.14   281.3 1050.74   290.9 1060.87
   292.8 1062.28   344.7 1096.37   363.3 1105.81   372.9  1109.4   382.2 1111.31
   387.4 1113.19   416.7 1133.13     434 1143.76   445.3 1148.54   458.4 1151.97
#Mann= 6 ,-1,0
       0      .1       0      60     .06       0     220     .05       0
     240      .1       0   260.7    .045       0  274.47      .1       0
Bank Sta=260.7,274.47
XS Rating Curve= 0 ,0
Exp/Cntr(USF)=0,0
Exp/Cntr=0.3,0.1

Type RM Length L Ch R = 1 ,1570    ,540.1,543.1,543.8
XS GIS Cut Line= 3
1691918.42358359411991.4273093421692146.85726115 411818.30941021
 1692201.1486733411735.335742579
#Sta/Elev= 30
       0 1056.16    42.3 1053.67    67.4  1050.5    87.4 1049.14   103.2  1048.9
   140.3 1049.36   147.7 1048.44   157.4  1046.3   167.7 1045.14   172.61043.604
   177.4 1042.61   182.8 1042.43   188.9 1043.61   194.6 1045.24   210.1 1045.61
     226 1046.51   231.7 1047.49   236.6 1049.61   240.2 1051.95   243.1 1054.45
   248.8 1061.51   253.1 1064.73   263.1 1069.43   273.1 1074.78   282.9 1079.51
   322.2 1095.21   341.3 1103.57     361 1108.39     370  1109.9   385.8 1115.56
#Mann= 4 ,-1,0
       0     .05       0     120      .1       0   172.6    .045       0
   188.9      .1       0
Bank Sta=172.6,188.9
XS Rating Curve= 0 ,0
Exp/Cntr(USF)=0,0
Exp/Cntr=0.3,0.1

Type RM Length L Ch R = 1 ,1027    ,505.8,505,504.1
XS GIS Cut Line= 3
1692211.57564773412382.2030760661692283.48615967412344.403960811
1692507.51506228412238.382052172
#Sta/Elev= 30
       0 1052.04    27.7 1051.01      64 1049.12   112.9 1047.66   157.2 1045.96
     166 1045.23   180.7 1042.44   192.8 1041.31   198.8 1041.19   210.3 1040.29
   213.8 1040.74   215.61041.214   219.8 1042.58   222.8 1043.89   225.8  1045.9
     228 1047.68   230.5 1050.22   236.8 1056.09   243.8 1063.39   254.5 1073.86
   258.8 1077.28   263.4 1080.09   272.2 1086.33   276.6 1089.22   285.5 1094.62
   297.9 1101.21   303.2 1103.44   312.1 1106.67   316.5  1108.6   329.1 1114.82
#Mann= 5 ,-1,0
       0     .06       0      50     .05       0  161.24      .1       0
   198.8    .045       0   215.6      .1       0
Bank Sta=198.8,215.6
XS Rating Curve= 0 ,0
Exp/Cntr(USF)=0,0
Exp/Cntr=0.3,0.1

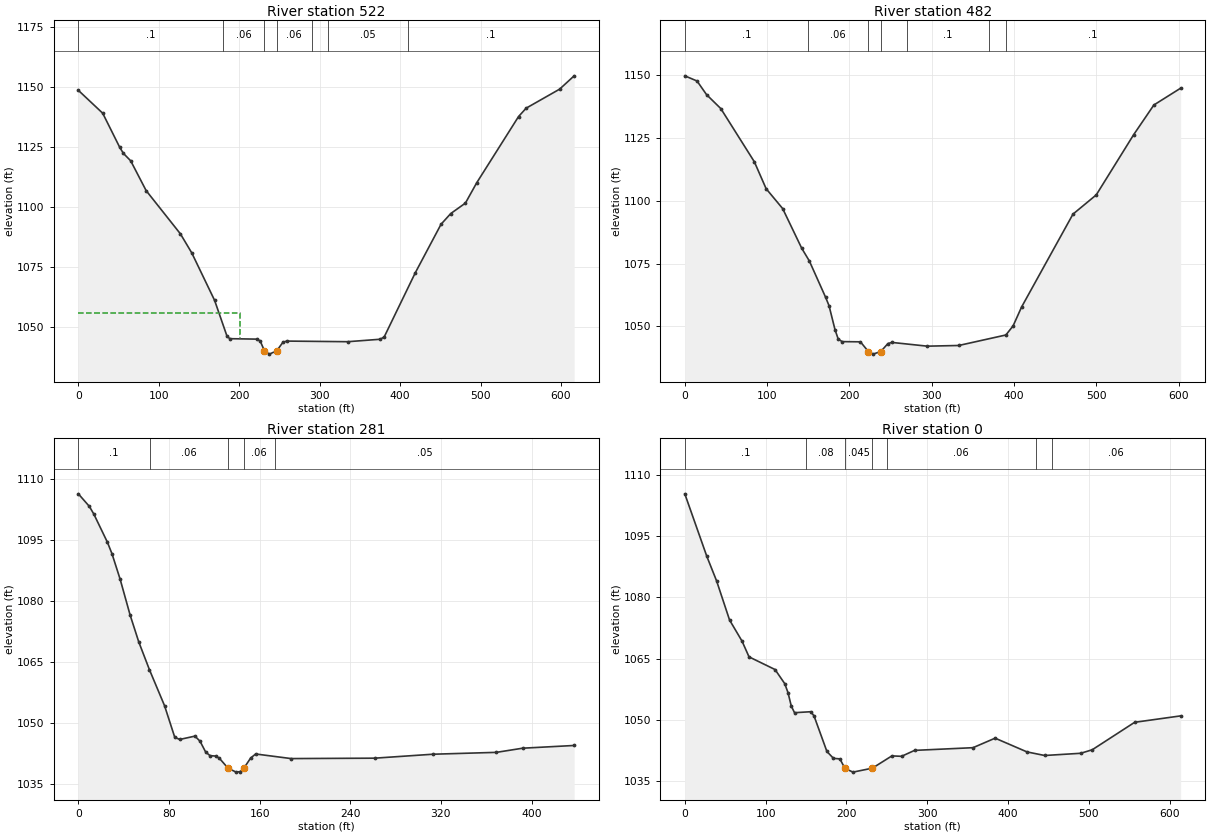
Type RM Length L Ch R = 1 ,522     ,39.9,40.1,39.7
XS GIS Cut Line= 2
1692404.70886675412870.8759603811692926.59091836412542.937336642
#Sta/Elev= 30
       0 1148.54    30.3 1138.99    51.3 1124.87      56 1122.26    65.1 1119.14
    84.3 1106.72   126.9 1088.69     141 1080.76   169.4 1060.96   184.8 1046.05
   188.3 1044.98   222.4 1044.79   226.1 1043.99   231.41039.923   237.5 1038.54
   246.61039.924   254.4  1043.5   259.1 1043.98   334.9 1043.72   375.5 1044.75
   380.3 1045.75     419 1072.53   450.9 1092.68     463 1097.16   481.2 1101.51
   495.3 1110.01   547.3 1137.61   556.7 1141.09   598.3 1149.02   616.4 1154.58
#Mann= 7 ,-1,0
       0      .1       0     180     .06       0   231.4    .045       0
   246.6     .06       0     290      .1       0     310     .05       0
     410      .1       0
#XS Ineff= 2 , 0
          200.65 1055.55
Permanent Ineff=
       F       F
Bank Sta=231.4,246.6
XS Rating Curve= 0 ,0
Exp/Cntr(USF)=0,0
Exp/Cntr=0.3,0.1

Type RM Length L Ch R = 1 ,482     ,199.3,200.8,201.1
XS GIS Cut Line= 2
 1692429.3167793412906.2964935321692934.02198786412577.409090858
#Sta/Elev= 30
       0 1149.75    14.9 1147.68    26.4 1142.27    43.8 1136.69    84.5 1115.53
    98.8 1104.82   118.9  1096.9     142 1081.14   151.3 1076.06     171 1061.64
   175.2 1058.28   182.5  1048.7   186.4 1044.95   191.2 1043.94   213.4 1043.86
     223    1040   228.8 1038.96   238.11040.005   246.8 1043.16   251.6 1043.62
   294.6 1042.13   332.8  1042.4   390.1 1046.58   398.9 1050.22   409.2 1057.73
   471.6 1094.69   499.9 1102.35   545.4 1126.35   569.9 1138.14   602.4 1144.83
#Mann= 7 ,-1,0
       0      .1       0     150     .06       0     223    .045       0
   238.1     .06       0     270      .1       0     370     .05       0
     390      .1       0
Bank Sta=223,238.1
XS Rating Curve= 0 ,0
Exp/Cntr(USF)=0,0
Exp/Cntr=0.3,0.1

Type RM Length L Ch R = 1 ,281     ,267.2,281,279.6
XS GIS Cut Line= 3
1692590.38212419412992.3835086651692643.64917008412991.359142398
1692987.83623581  412820.2899758
#Sta/Elev= 30
       0 1106.42     9.7 1103.34    13.7 1101.43    25.7  1094.5    29.7 1091.69
    36.9 1085.43    45.7 1076.63    53.3 1070.05    62.7 1063.23    76.1 1054.34
    85.1 1046.58    89.5 1046.05   102.9 1046.87   107.4 1045.62   112.4 1042.94
   116.3 1042.06   121.4 1041.97   124.4 1041.45   132.21038.971   139.3 1038.02
   143.1 1038.16  146.06 1038.98   152.1 1041.49   156.5 1042.48   187.8 1041.35
   261.6 1041.45   312.9 1042.42     369 1042.88   392.1  1043.9   437.6 1044.57
#Mann= 5 ,-1,0
       0      .1       0   63.28     .06       0   132.2    .045       0
  146.06     .06       0  173.28     .05       0
Bank Sta=132.2,146.06
XS Rating Curve= 0 ,0
Exp/Cntr(USF)=0,0
Exp/Cntr=0.3,0.1

Type RM Length L Ch R = 1 ,0       ,64.7,65.2,66.2
XS GIS Cut Line= 4
1692504.92118967413190.6109165341692887.42735311413225.987209106
 1693041.5103269413125.6751063511693084.34001617 413109.82812132
#Sta/Elev= 30
       0 1105.32    27.3    1090    39.4 1083.99    55.4 1074.45    70.9 1069.26
    79.5 1065.43   111.7 1062.33   123.7 1058.88   127.7  1056.7   131.8  1053.4
   135.8 1051.77   155.9 1052.01   159.9 1051.01   175.9 1042.28     184  1040.6
     192 1040.47   198.11038.174   208.1 1037.23   232.2  1038.2   256.3  1041.2
   268.3  1041.1   284.4 1042.55   356.7 1043.21   384.1 1045.54   423.5 1042.18
   445.4  1041.3     490 1041.84   504.3  1042.7   556.8 1049.42   613.7 1050.99
#Mann= 7 ,-1,0
       0      .1       0     150     .08       0   198.1    .045       0
   232.2     .08       0     250     .06       0  434.14     .05       0
  454.14     .06       0
Bank Sta=198.1,232.2
XS Rating Curve= 0 ,0
Exp/Cntr=0.3,0.1
LCMann Table=0

Chan Stop Cuts=-1
Use User Specified Reach Order=0
Composite Channel Slope=5